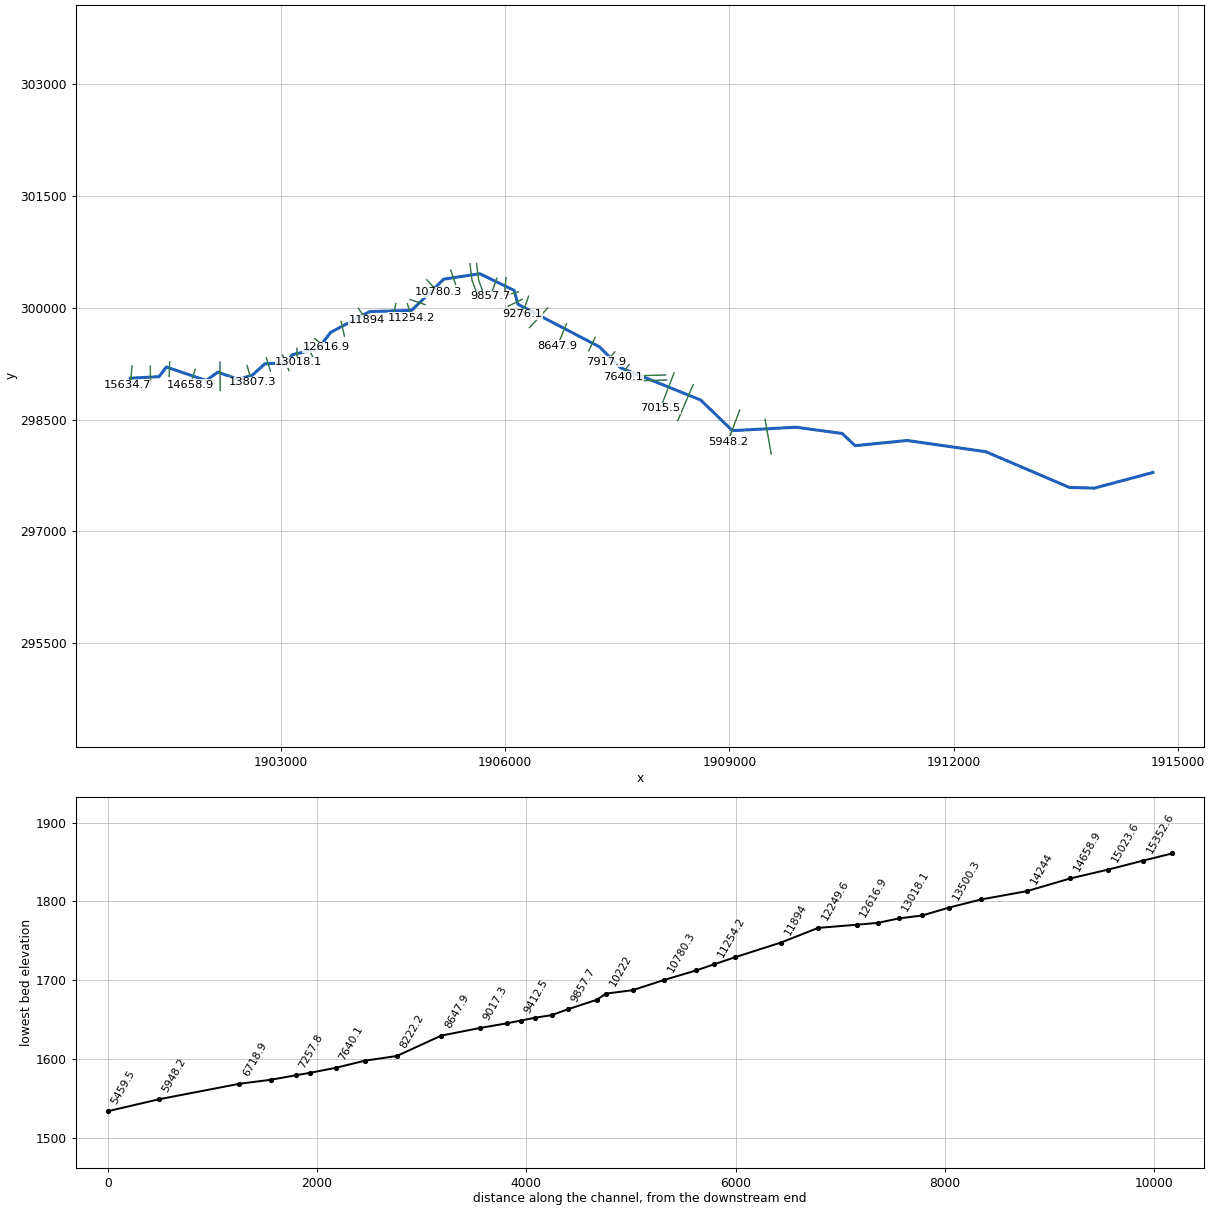
--- FLAGRN.prj (project) ---

Proj Title=FLAGRN
Current Plan=p01
Geom File=g01
Flow File=f01
Plan File=p01
DSS Export Rating Curves=0
DSS Export Rating Curve Sorted=0
DSS Export Volume Flow Curves=0
DXF OffsetX=0
DXF OffsetY=0
DXF ScaleX=0
DXF ScaleY=0

--- FLAGRN.p01 (plan) ---

Plan Title=Floodplain
Program Version=4.00
Geom File=g01
Flow File=f01
K Sum by GR=0
Std Step Tol=0.01
Critical Tol=0.01
Num of Std Step Trials=20
Max Error Tol=0.3
Flow Tol Ratio=0.001
Split Flow NTrial=30
Split Flow Tol=0.02
Split Flow Ratio=0.02
Log Output Level=0
Friction Slope Method=1
Unsteady Friction Slope Method=2
Unsteady Bridges Friction Slope Method=1
Global Log Level=0
CheckData=False
Run HTab=0
Run UNet=0
Run PostProcess=0
UNET Theta=0
UNET Theta Warmup=0
UNET ZTol=0
UNET ZSATol=0
UNET MxIter=0
UNET MaxInSteps=0
UNET DtIC=0
UNET DtMin=0
UNET MaxCRTS=0
UNET WFStab=0
UNET SFStab=0
UNET WFX=0
UNET SFX=0
UNET DSS MLevel=0
UNET DZMax Abort=0
UNET Convert EG Bridges=0
UNET Use Existing IB Tables=0
UNET Froude Limit=0
UNET Froude Power=0
Write IC File=0
Echo Input=False
Echo Output=False
Write Detailed=0

--- FLAGRN.f01 (steady flow) ---

Flow Title=NFF Regression Equation
Program Version=4.10
Number of Profiles= 1
Profile Names=P100yr
River Rch & RM=FLAGRN,Main            ,15634.7
556.4637
River Rch & RM=FLAGRN,Main            ,13245.6
600.9098
River Rch & RM=FLAGRN,Main            ,10132.1
652.2942
River Rch & RM=FLAGRN,Main            ,9857.7
869.9883
River Rch & RM=FLAGRN,Main            ,7391.3
922.1387
River Rch & RM=FLAGRN,Main            ,6718.9
1196.499
River Rch & RM=FLAGRN,Main            ,634.3
1299.236
Boundary for River Rch & Prof#=FLAGRN,Main            , 1
Up Type= 0
Dn Type= 3
Dn Slope=0.01764
DSS Import GetInterval= 0
DSS Import GetPeak= 0
DSS Import FillOption= 0

--- FLAGRN.g01 (geometry) ---

Geom Title=USGS 10m DEM
Program Version=4.10

River Reach=FLAGRN          ,Main
Reach XY= 30
      1900987.05      299056.449     1901371.727      299076.829
      1901471.08      299206.753     1902002.267      299025.228
     1902158.912       299137.97     1902429.582      299040.594
     1902620.015       299097.21     1902788.151      299250.061
     1903076.022      299262.799     1903152.448      299372.342
     1903503.096      299451.629      1903665.01      299670.403
       1904189.8      299950.631     1904749.747      299966.935
     1905181.658      300386.316     1905661.761      300458.608
     1906121.335      300234.425     1906171.776      300048.456
     1907262.117      299476.791     1907542.855      299197.073
     1908615.363      298763.993     1909039.272      298352.822
     1909890.146      298398.678     1910508.685      298314.609
     1910679.369      298151.568     1911377.392      298220.351
     1912429.011      298070.047     1913543.299      297591.621
     1913879.572      297581.431     1914663.719      297791.741

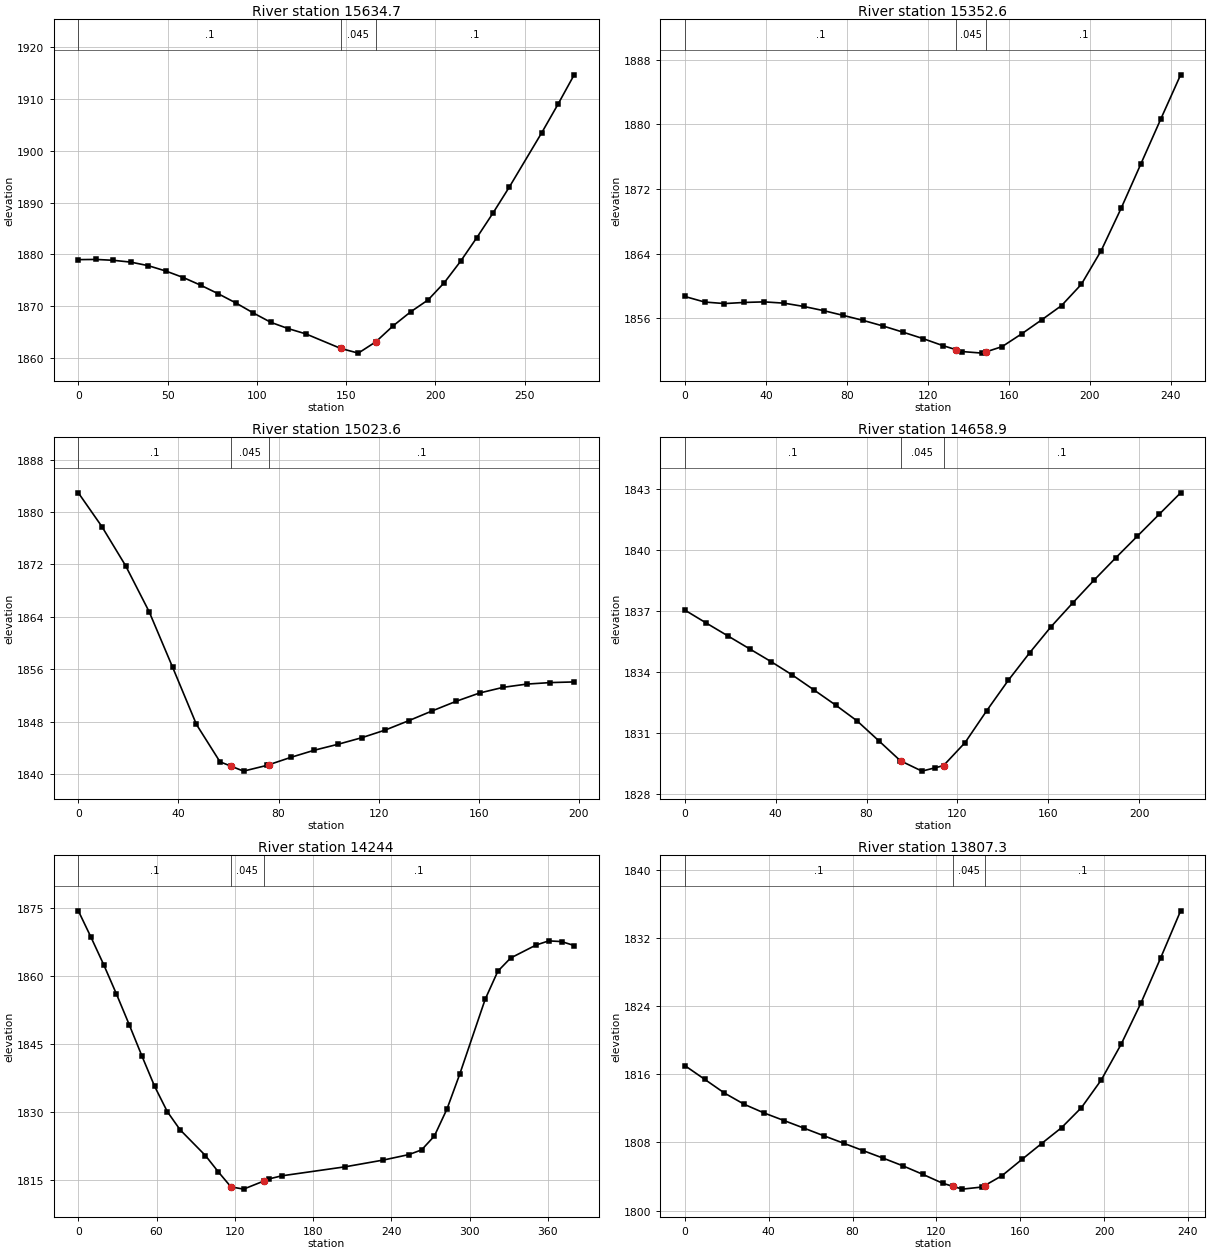
Type RM Length L Ch R = 1 ,15634.7 ,293.8,282,300.4
XS GIS Cut Line= 3
     1901010.294      299220.645     1900994.669      299025.333
      1900945.19      298960.229
#Sta/Elev= 28
       0    1879     9.8 1879.04    19.6 1878.87    29.4 1878.52    39.2 1877.83
      49  1876.8    58.8 1875.54    68.6 1874.05    78.4  1872.4    88.2 1870.64
      98  1868.7   107.8 1866.89   117.6 1865.67   127.4 1864.66     147 1861.84
   156.8 1860.94   166.6 1863.12   176.3 1866.21   186.1 1868.91   195.9 1871.22
     205 1874.57   214.1 1878.69   223.2 1883.26   232.3 1888.03   241.4 1893.03
   259.5 1903.49   268.6 1908.99   277.7  1914.7
#Mann= 3 , 0 , 0
       0      .1       0     147    .045       0   166.6      .1       0
Bank Sta=147,166.6
XS Rating Curve= 0 ,0
Exp/Cntr=0.3,0.1

Type RM Length L Ch R = 1 ,15352.6 ,330,329,328
XS GIS Cut Line= 2
     1901255.086      299218.041      1901257.69      298973.249
#Sta/Elev= 28
       0 1858.68     9.8 1857.99    19.6  1857.8    29.4 1857.94    39.2 1858.01
      49 1857.85    58.8 1857.44    68.6 1856.92    78.3 1856.33    88.1 1855.71
    97.9 1855.02   107.7 1854.26   117.5 1853.47   127.3  1852.6   133.9 1852.09
   137.1 1851.85   146.9 1851.66   148.9 1851.83   156.7 1852.47   166.5 1854.08
   176.3  1855.8     186 1857.55   195.8 1860.19   205.6 1864.37   215.4 1869.59
   225.2 1875.12     235 1880.66   244.8 1886.14
#Mann= 3 , 0 , 0
       0      .1       0   133.9    .045       0   148.9      .1       0
Bank Sta=133.9,148.9
XS Rating Curve= 0 ,0
Exp/Cntr=0.3,0.1

Type RM Length L Ch R = 1 ,15023.6 ,370.6,364.8,358.9
XS GIS Cut Line= 2
     1901515.503      299275.333      1901507.69      299077.416
#Sta/Elev= 24
       0 1882.92     9.4 1877.78    18.9  1871.8    28.3 1864.79    37.7  1856.3
    47.2  1847.6    56.6 1841.91    61.1 1841.23      66 1840.49    75.5 1841.38
    76.1 1841.46    84.9 1842.59    94.3 1843.68   103.8 1844.59   113.2 1845.58
   122.6 1846.75     132 1848.18   141.5 1849.69   150.9 1851.13   160.3  1852.4
   169.8 1853.27   179.2 1853.76   188.6 1853.99   198.1 1854.09
#Mann= 3 , 0 , 0
       0      .1       0    61.1    .045       0    76.1      .1       0
Bank Sta=61.1,76.1
XS Rating Curve= 0 ,0
Exp/Cntr=0.3,0.1

Type RM Length L Ch R = 1 ,14658.9 ,407.5,414.9,421.6
XS GIS Cut Line= 2
     1901856.648      299176.374     1901791.544      298968.041
#Sta/Elev= 26
       0 1837.04     9.5  1836.4      19 1835.77    28.5 1835.14      38 1834.51
    47.4 1833.85    56.9 1833.12    66.4 1832.38    75.9  1831.6    85.4 1830.63
    94.9 1829.65    95.1 1829.64   104.4 1829.14   110.1  1829.3   113.9 1829.41
   123.4 1830.54   132.9  1832.1   142.4 1833.59   151.8 1834.94   161.3 1836.23
   170.8 1837.39   180.3 1838.52   189.8 1839.61   199.3 1840.67   208.8 1841.73
   218.3 1842.79
#Mann= 3 , 0 , 0
       0      .1       0    95.1    .045       0   113.9      .1       0
Bank Sta=95.1,113.9
XS Rating Curve= 0 ,0
Exp/Cntr=0.3,0.1

Type RM Length L Ch R = 1 ,14244   ,429.6,436.7,443.1
XS GIS Cut Line= 2
     1902187.378      299272.729     1902189.982       298892.52
#Sta/Elev= 30
       0 1874.31     9.8 1868.44    19.5 1862.42    29.2 1856.01      39 1849.25
    48.8 1842.31    58.5 1835.66    68.2  1830.1      78  1826.1    97.5  1820.4
   107.2 1816.87     117 1813.52   126.7 1813.02   142.3 1814.81   146.2 1815.27
     156 1815.95   204.7 1817.94     234 1819.43   253.5 1820.63   263.2 1821.66
     273 1824.71   282.7 1830.68   292.5 1838.37     312 1854.85   321.7 1861.02
   331.5 1863.92     351 1866.78   360.7 1867.69   370.5 1867.54   380.2 1866.67
#Mann= 3 , 0 , 0
       0      .1       0     117    .045       0   142.3      .1       0
Bank Sta=117,142.3
XS Rating Curve= 0 ,0
Exp/Cntr=0.3,0.1

Type RM Length L Ch R = 1 ,13807.3 ,306.4,307.1,307.5
XS GIS Cut Line= 2
     1902549.357      299225.854     1902617.065      298999.291
#Sta/Elev= 28
       0 1817.04     9.5 1815.42    18.9 1813.81    28.4 1812.48    37.8 1811.47
    47.3 1810.58    56.8 1809.69    66.2  1808.8    75.7 1807.92    85.1 1807.04
    94.6 1806.16     104 1805.26   113.5 1804.26     123 1803.21     128 1802.84
   132.4 1802.52   141.9 1802.77     143 1802.93   151.3  1804.1   160.8 1806.01
   170.2 1807.88   179.7 1809.74   189.2  1812.1   198.6 1815.33   208.1 1819.53
   217.6  1824.4     227  1829.7   236.5 1835.22
#Mann= 3 , 0 , 0
       0      .1       0     128    .045       0     143      .1       0
Bank Sta=128,143
XS Rating Curve= 0 ,0
Exp/Cntr=0.3,0.1

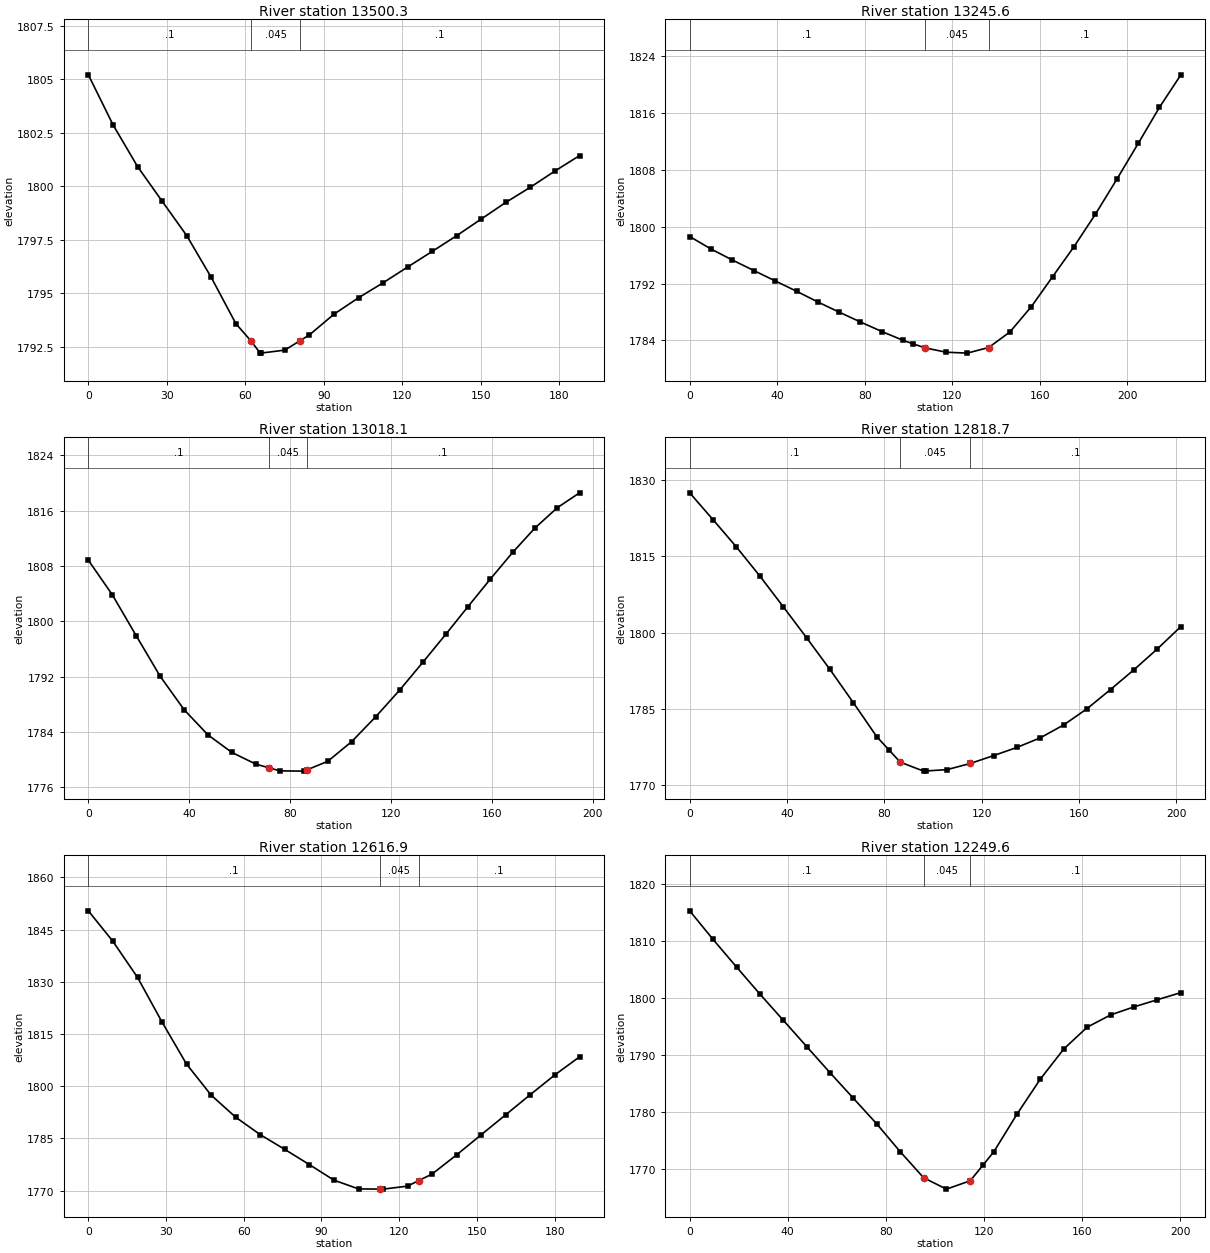
Type RM Length L Ch R = 1 ,13500.3 ,250.6,254.6,257.3
XS GIS Cut Line= 2
     1902807.169      299332.624     1902861.857      299152.937
#Sta/Elev= 24
       0 1805.21     9.4 1802.88    18.8 1800.92    28.2  1799.3    37.6 1797.69
      47 1795.73    56.4 1793.57   62.25 1792.75    65.7 1792.19    65.9 1792.19
    75.1 1792.33    80.9 1792.77    84.5 1793.04    93.9 1794.01   103.3 1794.78
   112.7 1795.48   122.1 1796.22   131.5 1796.95   140.9 1797.69   150.3 1798.47
   159.6 1799.24     169 1799.95   178.4 1800.71   187.8 1801.43
#Mann= 3 , 0 , 0
       0      .1       0   62.25    .045       0    80.9      .1       0
Bank Sta=62.25,80.9
XS Rating Curve= 0 ,0
Exp/Cntr=0.3,0.1

Type RM Length L Ch R = 1 ,13245.6 ,239.3,227.6,215.5
XS GIS Cut Line= 2
     1903025.919      299366.479     1903109.253      299158.145
#Sta/Elev= 25
       0 1798.63     9.8 1796.86    19.5 1795.32    29.3 1793.84      39 1792.39
    48.8 1790.93    58.5 1789.42    68.3 1787.98      78  1786.6    87.8 1785.25
    97.6    1784   102.1 1783.52   107.3 1782.97   117.1 1782.34   126.8 1782.21
   136.6    1783   146.3 1785.19   156.1 1788.76   165.8 1792.97   175.6 1797.21
   185.4 1801.79   195.1 1806.67   204.9 1811.73   214.6 1816.81   224.4  1821.4
#Mann= 3 , 0 , 0
       0      .1       0   107.3    .045       0   136.6      .1       0
Bank Sta=107.3,136.6
XS Rating Curve= 0 ,0
Exp/Cntr=0.3,0.1

Type RM Length L Ch R = 1 ,13018.1 ,190.9,199.4,208
XS GIS Cut Line= 3
     1903216.023      299457.624     1903218.628      299324.812
     1903242.065       299267.52
#Sta/Elev= 24
       0 1808.82     9.5 1803.83      19 1797.89    28.5 1792.03      38  1787.2
    47.4 1783.58    56.9 1781.04    66.4 1779.35    71.5 1778.83    75.9 1778.38
    85.4 1778.34    86.5  1778.5    94.9 1779.76   104.4 1782.61   113.9 1786.19
   123.4 1790.05   132.8 1794.16   141.7 1798.12   150.5 1802.12   159.4 1806.12
   168.2 1809.95     177 1813.46   185.9 1816.41   194.7 1818.56
#Mann= 3 , 0 , 0
       0      .1       0    71.5    .045       0    86.5      .1       0
Bank Sta=71.5,86.5
XS Rating Curve= 0 ,0
Exp/Cntr=0.3,0.1

Type RM Length L Ch R = 1 ,12818.7 ,189.9,201.8,213.6
XS GIS Cut Line= 2
      1903351.44      299514.916     1903432.169       299330.02
#Sta/Elev= 24
       0 1827.51     9.6 1822.22    19.2 1816.86    28.8 1811.16    38.4 1805.13
      48 1799.02    57.6 1792.79    67.2 1786.26    76.9 1779.52      82 1776.87
    86.5 1774.54    96.1 1772.77      97  1772.8   105.7 1773.06   115.3 1774.28
   124.9 1775.83   134.5 1777.44   144.1 1779.33   153.7 1781.87   163.3 1785.06
   172.9 1788.82   182.5  1792.7   192.1 1796.79   201.8  1801.2
#Mann= 3 , 0 , 0
       0      .1       0    86.5    .045       0   115.3      .1       0
Bank Sta=86.5,115.3
XS Rating Curve= 0 ,0
Exp/Cntr=0.3,0.1

Type RM Length L Ch R = 1 ,12616.9 ,383.6,367.3,351.1
XS GIS Cut Line= 2
     1903453.003      299587.833     1903604.044      299473.249
#Sta/Elev= 23
       0 1850.41     9.5 1841.62      19 1831.25    28.4  1818.5    37.9 1806.36
    47.4 1797.44    56.9 1791.07    66.4 1786.06    75.8 1781.85    85.3 1777.48
    94.8    1773   104.3 1770.48   112.5 1770.43   113.8 1770.42   123.2 1771.28
   127.5 1772.86   132.7 1774.76   142.2 1780.29   151.7 1786.08   161.2 1791.85
   170.6 1797.58   180.1 1803.26   189.6 1808.44
#Mann= 3 , 0 , 0
       0      .1       0   112.5    .045       0   127.5      .1       0
Bank Sta=112.5,127.5
XS Rating Curve= 0 ,0
Exp/Cntr=0.3,0.1

Type RM Length L Ch R = 1 ,12249.6 ,347.4,355.6,362.5
XS GIS Cut Line= 2
     1903807.169      299816.999      1903851.44      299621.687
#Sta/Elev= 23
       0 1815.33     9.5 1810.32    19.1 1805.45    28.6 1800.71    38.2 1796.07
    47.7 1791.47    57.2 1786.88    66.8 1782.35    76.3 1777.86    85.8 1773.01
    95.4  1768.4   104.7  1766.4   114.4 1767.87   119.7 1770.67     124 1772.95
   133.5  1779.6     143 1785.75   152.6 1791.06   162.1 1794.87   171.7 1797.04
   181.2 1798.44   190.7  1799.7   200.3 1800.95
#Mann= 3 , 0 , 0
       0      .1       0    95.4    .045       0   114.4      .1       0
Bank Sta=95.4,114.4
XS Rating Curve= 0 ,0
Exp/Cntr=0.3,0.1

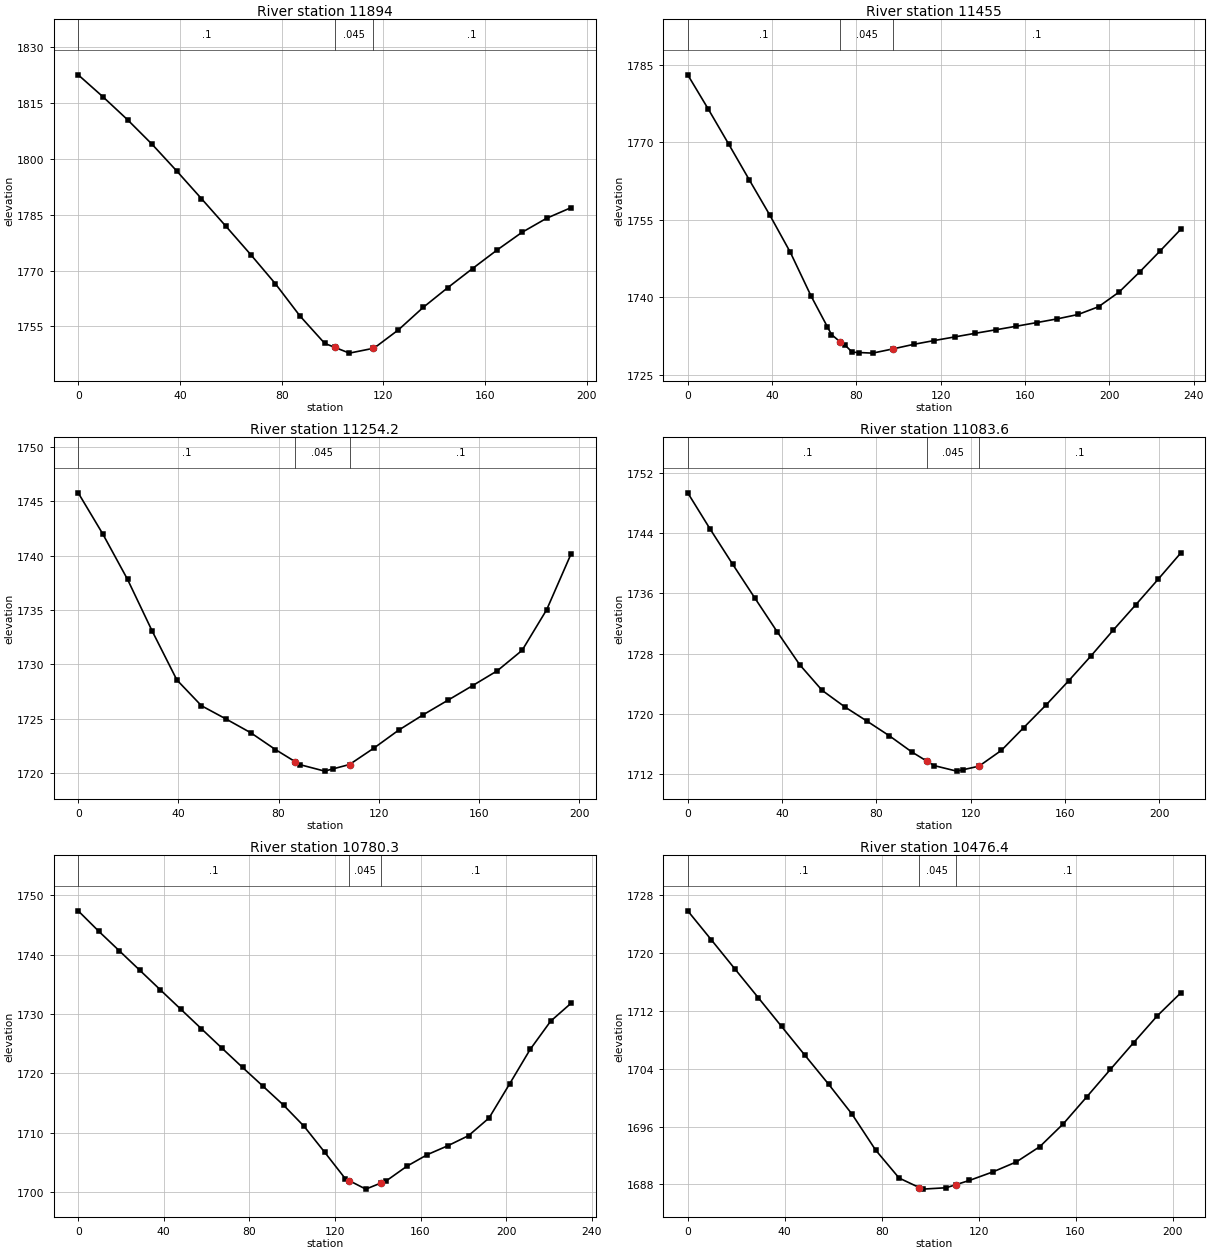
Type RM Length L Ch R = 1 ,11894   ,457.9,439,420.2
XS GIS Cut Line= 2
      1904038.94      299991.479     1904153.523      299835.229
#Sta/Elev= 23
       0 1822.64     9.7 1816.75    19.4 1810.56    29.1 1803.92    38.8 1796.73
    48.4 1789.38    58.1 1781.89    67.8 1774.31    77.5 1766.47    87.2 1757.77
    96.9 1750.42   100.9 1749.34   106.6  1747.8   115.9 1749.08   116.3 1749.14
   125.9 1754.07   135.6 1760.09   145.3 1765.42     155 1770.54   164.7 1775.55
   174.4 1780.26   184.1 1784.06   193.8 1786.94
#Mann= 3 , 0 , 0
       0      .1       0   100.9    .045       0   115.9      .1       0
Bank Sta=100.9,115.9
XS Rating Curve= 0 ,0
Exp/Cntr=0.3,0.1

Type RM Length L Ch R = 1 ,11455   ,188.9,200.8,212.7
XS GIS Cut Line= 2
      1904538.94      300059.187     1904492.065       299830.02
#Sta/Elev= 29
       0 1783.03     9.8 1776.36    19.5 1769.57    29.2  1762.7      39 1755.83
    48.7 1748.65    58.5 1740.22    66.2  1734.3    68.2 1732.76   72.18 1731.39
   74.65 1730.72      78 1729.34    81.2 1729.28    87.7 1729.16    97.5 1729.99
   107.2 1730.86     117  1731.6   126.7  1732.3   136.4    1733   146.2 1733.68
   155.9 1734.37   165.7 1735.08   175.4  1735.8   185.2 1736.64   194.9 1738.14
   204.7    1741   214.4 1744.87   224.2 1748.98   233.9 1753.13
#Mann= 3 , 0 , 0
       0      .1       0   72.18    .045       0    97.5      .1       0
Bank Sta=72.18,97.5
XS Rating Curve= 0 ,0
Exp/Cntr=0.3,0.1

Type RM Length L Ch R = 1 ,11254.2 ,148.9,170.6,192.2
XS GIS Cut Line= 2
     1904692.586      300056.583     1904752.482      299869.083
#Sta/Elev= 23
       0 1745.78     9.8    1742    19.7 1737.81    29.5 1733.07    39.4 1728.55
    49.2 1726.18      59 1724.96    68.9 1723.69    78.7 1722.15    86.6 1721.03
    88.6 1720.75    98.4 1720.16   101.6 1720.36   108.3 1720.77   118.1 1722.29
   127.9 1723.93   137.8 1725.36   147.6 1726.69   157.5 1728.04   167.3  1729.4
   177.2 1731.28     187 1735.02   196.8 1740.19
#Mann= 3 , 0 , 0
       0      .1       0    86.6    .045       0   108.3      .1       0
Bank Sta=86.6,108.3
XS Rating Curve= 0 ,0
Exp/Cntr=0.3,0.1

Type RM Length L Ch R = 1 ,11083.6 ,313.7,303.3,292.8
XS GIS Cut Line= 2
     1904731.648       300111.27     1904929.565      300043.562
#Sta/Elev= 25
       0 1749.36     9.5 1744.55      19 1739.91    28.5 1735.38      38 1730.89
    47.5 1726.54      57 1723.14    66.6 1720.95    76.1 1719.04    85.6 1717.09
    95.1 1714.95   101.6 1713.71   104.6 1713.14   114.1 1712.41   116.6 1712.58
   123.6 1713.07   133.1 1715.17   142.6  1718.2   152.1 1721.21   161.6 1724.39
   171.2 1727.74   180.6 1731.15   190.2 1734.53   199.7 1737.92   209.2 1741.37
#Mann= 3 , 0 , 0
       0      .1       0   101.6    .045       0   123.6      .1       0
Bank Sta=101.6,123.6
XS Rating Curve= 0 ,0
Exp/Cntr=0.3,0.1

Type RM Length L Ch R = 1 ,10780.3 ,314.2,303.9,294
XS GIS Cut Line= 2
     1904953.003      300376.895     1905109.253      300207.624
#Sta/Elev= 27
       0 1747.37     9.6 1743.93    19.2 1740.64    28.8 1737.35    38.4 1734.05
      48 1730.77    57.6 1727.49    67.2 1724.22    76.8 1720.98    86.4  1717.8
      96 1714.61   105.6 1711.04   115.2 1706.68   124.8 1702.24   126.6 1701.91
   134.4 1700.47   141.6 1701.52     144 1701.87   153.6 1704.33   163.2 1706.29
   172.8 1707.79   182.4 1709.48     192 1712.46   201.6  1718.2   211.2 1724.01
   220.8 1728.78   230.4 1731.82
#Mann= 3 , 0 , 0
       0      .1       0   126.6    .045       0   141.6      .1       0
Bank Sta=126.6,141.6
XS Rating Curve= 0 ,0
Exp/Cntr=0.3,0.1

Type RM Length L Ch R = 1 ,10476.4 ,258.9,254.4,249.6
XS GIS Cut Line= 2
     1905273.315      300507.104     1905338.419      300314.395
#Sta/Elev= 24
       0 1725.78     9.7 1721.79    19.4 1717.78    29.1 1713.79    38.7 1709.82
    48.4 1705.82    58.1 1701.85    67.8  1697.7    77.5 1692.76    87.2 1688.89
    95.5 1687.58    96.9 1687.36   106.6 1687.55   110.5 1687.96   116.2 1688.56
   125.9 1689.74   135.6 1691.12   145.3 1693.24     155  1696.4   164.7 1700.13
   174.4  1703.9     184  1707.6   193.7 1711.28   203.4 1714.45
#Mann= 3 , 0 , 0
       0      .1       0    95.5    .045       0   110.5      .1       0
Bank Sta=95.5,110.5
XS Rating Curve= 0 ,0
Exp/Cntr=0.3,0.1

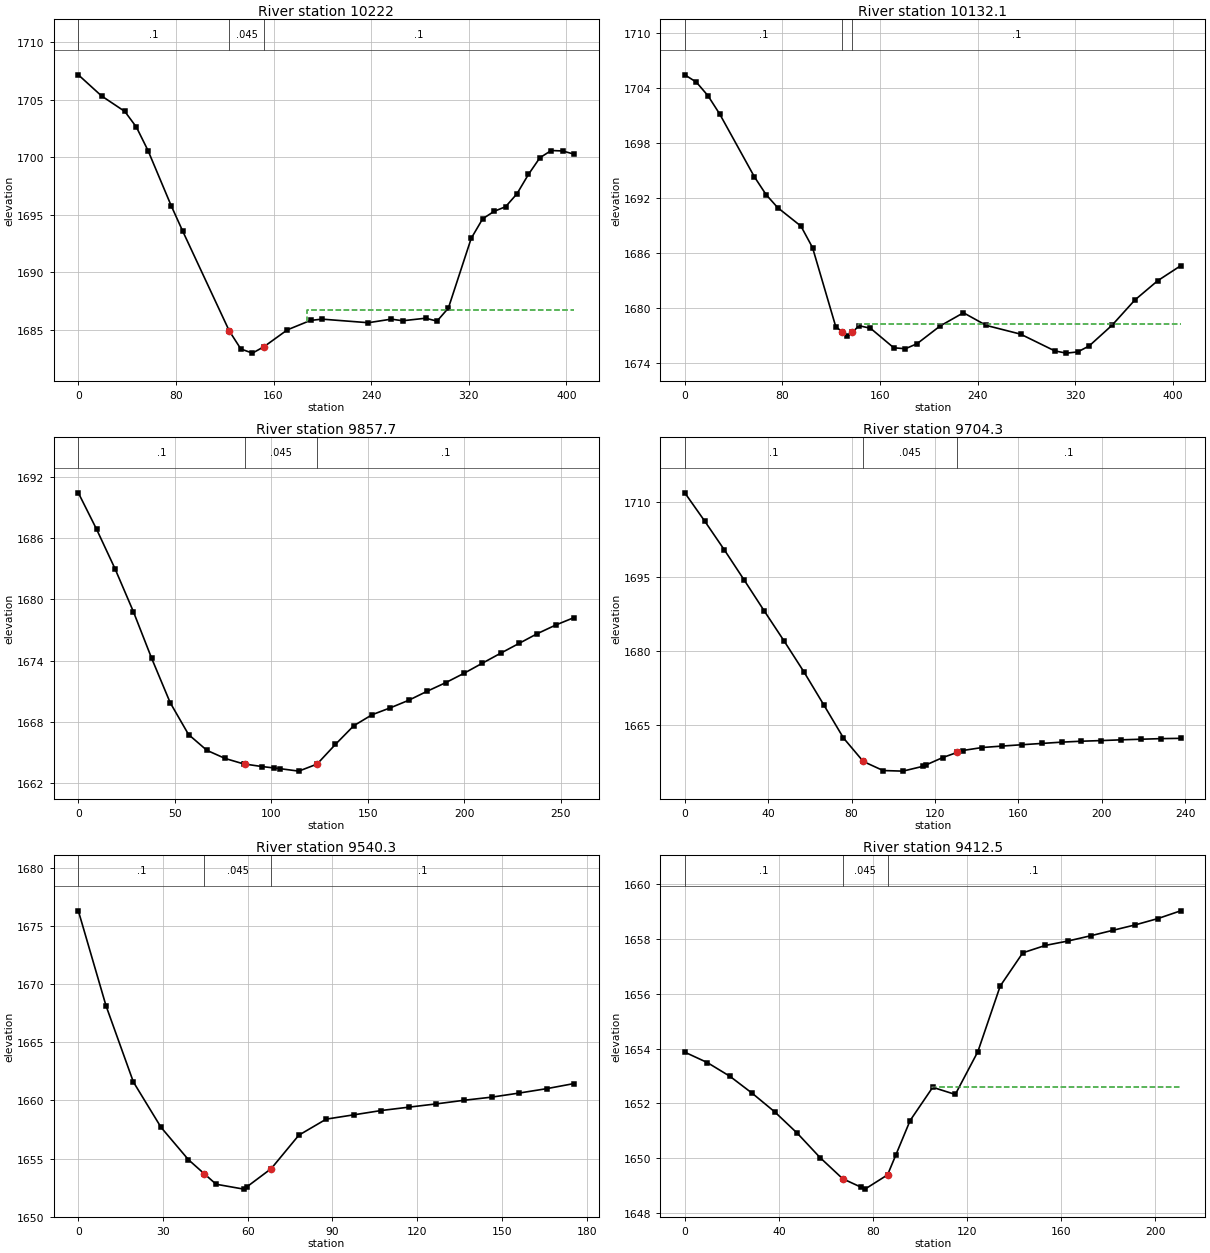
Type RM Length L Ch R = 1 ,10222   ,89.9,89.9,89.9
XS GIS Cut Line= 3
     1905530.086      300591.999     1905558.732      300365.437
     1905621.232       300198.77
#Sta/Elev= 30
       0 1707.15      19 1705.32    38.1 1703.97    47.6 1702.61    57.1 1700.58
    76.1 1695.79    85.6 1693.57   123.7 1684.92   133.2 1683.35   142.7 1682.99
   152.2 1683.55   171.3 1685.01   190.3 1685.83   199.8 1685.94   237.7 1685.63
   256.5 1685.94   265.8  1685.8   284.6 1686.02     294 1685.77   303.3  1686.9
     322 1692.95   331.4 1694.65   340.8  1695.3   350.2  1695.7   359.5 1696.82
   368.9  1698.5   378.3 1699.95   387.6 1700.58     397 1700.54   406.4 1700.26
#Mann= 3 , 0 , 0
       0      .1       0   123.7    .045       0   152.2      .1       0
#XS Ineff= 2 , 0
                          187.32         1686.74
Permanent Ineff=
       F       F
Bank Sta=123.7,152.2
XS Rating Curve= 0 ,0
Exp/Cntr=0.3,0.1

Type RM Length L Ch R = 1 ,10132.1 ,284.7,274.4,264
XS GIS Cut Line= 3
     1905618.628      300594.604     1905647.273      300368.041
     1905709.773      300201.374
#Sta/Elev= 30
       0 1705.45     9.5 1704.65      19 1703.17    28.6 1701.18    57.1 1694.32
    66.6  1692.4    76.1 1690.98    95.2 1688.96   104.7 1686.62   123.7 1678.02
   128.9 1677.44   133.2 1676.97  137.32 1677.37   142.7 1678.11   152.2 1677.83
   171.3  1675.7   180.8  1675.6   190.3 1676.14   209.3 1678.08   228.4 1679.52
   247.1 1678.14   275.2 1677.19   303.3 1675.36   312.7 1675.12     322 1675.25
   331.4  1675.9   350.2 1678.16   368.9 1680.91   387.6 1683.01   406.4 1684.64
#Mann= 3 , 0 , 0
       0      .1       0   128.9    .045       0  137.32      .1       0
#XS Ineff= 2 , 0
                          142.25         1678.33
Permanent Ineff=
       F       F
Bank Sta=128.9,137.32
XS Rating Curve= 0 ,0
Exp/Cntr=0.3,0.1

Type RM Length L Ch R = 1 ,9857.7  ,147.8,153.4,159
XS GIS Cut Line= 2
     1905889.461      300396.687     1905803.818      300154.514
#Sta/Elev= 30
       0 1690.46     9.5 1686.87      19 1683.02    28.5 1678.82      38 1674.23
    47.6 1669.88    57.1 1666.76    66.6 1665.21    76.1 1664.41    85.6 1663.88
    86.4 1663.86    95.1 1663.62   101.4 1663.48   104.6 1663.41   114.2 1663.17
   123.7 1663.86   133.2 1665.79   142.7 1667.62   152.2  1668.7   161.7 1669.38
   171.2 1670.12   180.8 1671.01   190.3 1671.84   199.8 1672.76   209.3 1673.75
   218.8 1674.73   228.3 1675.69   237.8 1676.65   247.4  1677.5   256.9 1678.23
#Mann= 3 , 0 , 0
       0      .1       0    86.4    .045       0   123.7      .1       0
Bank Sta=86.4,123.7
XS Rating Curve= 0 ,0
Exp/Cntr=0.3,0.1

Type RM Length L Ch R = 1 ,9704.3  ,192.3,164,135.7
XS GIS Cut Line= 2
     1906011.857      300404.499     1905992.177      300167.504
#Sta/Elev= 28
       0 1711.92     9.5 1706.24      19 1700.38    28.5  1694.3      38 1688.14
    47.6 1682.02    57.1 1675.79    66.6 1669.15    76.1 1662.42    85.6 1657.68
    95.1 1655.85   104.6 1655.73   114.2  1656.7   115.7 1656.98   123.7 1658.47
   130.7 1659.52   133.2 1659.89   142.7  1660.5   152.2 1660.79   161.7 1661.06
   171.2 1661.32   180.7 1661.58   190.2 1661.77   199.8  1661.9   209.3 1662.05
   218.8 1662.17   228.3 1662.29   237.8 1662.35
#Mann= 3 , 0 , 0
       0      .1       0    85.6    .045       0   130.7      .1       0
Bank Sta=85.6,130.7
XS Rating Curve= 0 ,0
Exp/Cntr=0.3,0.1

Type RM Length L Ch R = 1 ,9540.3  ,123.3,127.8,132
XS GIS Cut Line= 2
     1906178.523      300216.999     1906009.253      300170.124
#Sta/Elev= 21
       0  1676.3     9.8 1668.14    19.5 1661.58    29.3 1657.68      39  1654.9
    44.6 1653.69    48.8 1652.79    58.6 1652.37    59.6 1652.55    68.3 1654.13
    78.1 1657.01    87.8 1658.39    97.6 1658.76   107.3 1659.13   117.1 1659.42
   126.8  1659.7   136.6 1660.01   146.4 1660.28   156.1 1660.63   165.9 1661.01
   175.6 1661.45
#Mann= 3 , 0 , 0
       0      .1       0    44.6    .045       0    68.3      .1       0
Bank Sta=44.6,68.3
XS Rating Curve= 0 ,0
Exp/Cntr=0.3,0.1

Type RM Length L Ch R = 1 ,9412.5  ,118.5,136.5,154.4
XS GIS Cut Line= 2
     1906229.251      300115.543     1906040.503      300021.687
#Sta/Elev= 25
       0 1653.87     9.6 1653.49    19.2 1652.99    28.7 1652.37    38.3 1651.69
    47.9 1650.91    57.5 1650.03    67.1 1649.26    74.7 1648.96    76.6 1648.88
    86.2  1649.4    89.7 1650.12    95.8 1651.38   105.4 1652.59     115 1652.33
   124.6 1653.89   134.1 1656.28   143.7 1657.49   153.3 1657.76   162.9 1657.92
   172.5 1658.11     182 1658.31   191.6 1658.51   201.2 1658.74   210.8 1659.02
#Mann= 3 , 0 , 0
       0      .1       0    67.1    .045       0    86.2      .1       0
#XS Ineff= 2 , 0
                          105.28          1652.6
Permanent Ineff=
       F       F
Bank Sta=67.1,86.2
XS Rating Curve= 0 ,0
Exp/Cntr=0.3,0.1

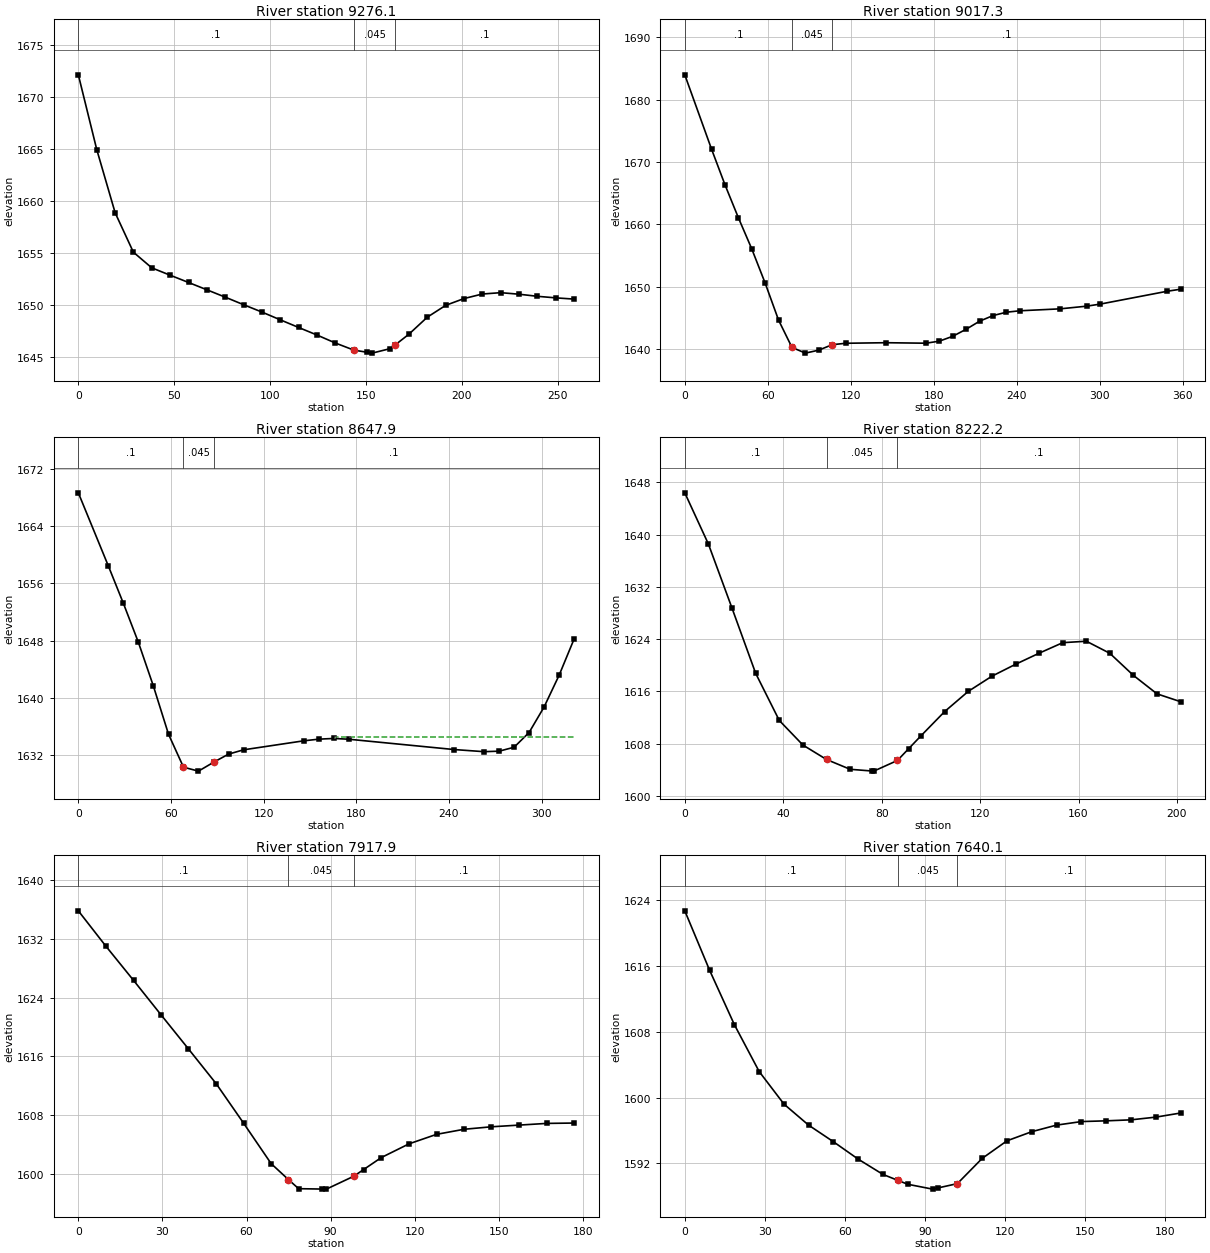
Type RM Length L Ch R = 1 ,9276.1  ,268.2,258.7,249.3
XS GIS Cut Line= 2
      1906313.94      300157.104     1906230.607      299912.312
#Sta/Elev= 30
       0 1672.15     9.6 1664.96    19.2 1658.87    28.7 1655.08    38.3 1653.57
    47.9 1652.86    57.5 1652.16      67 1651.46    76.6 1650.75    86.2 1650.02
    95.8 1649.31   105.4 1648.56   114.9 1647.83   124.5  1647.1   134.1 1646.33
   143.7 1645.65   150.4 1645.45   153.2 1645.36   162.8  1645.8   165.4 1646.17
   172.4 1647.18     182 1648.82   191.6 1649.96   201.1 1650.61   210.7 1651.05
   220.3 1651.18   229.9 1651.03   239.4 1650.83     249 1650.68   258.6 1650.56
#Mann= 3 , 0 , 0
       0      .1       0   143.7    .045       0   165.4      .1       0
Bank Sta=143.7,165.4
XS Rating Curve= 0 ,0
Exp/Cntr=0.3,0.1

Type RM Length L Ch R = 1 ,9017.3  ,361.3,369.4,377.5
XS GIS Cut Line= 2
     1906570.247       299998.63     1906326.961      299735.229
#Sta/Elev= 26
       0 1683.99    19.4 1672.04    29.1 1666.34    38.8 1661.05    48.4  1656.1
    58.2 1650.55    67.8 1644.67    77.5 1640.29    87.2 1639.37    96.9 1639.85
   106.6 1640.72   116.3 1640.95   145.4 1641.04   174.4 1640.96   184.1 1641.29
   193.8 1642.07   203.5  1643.2   213.2 1644.49   222.9 1645.39   232.6 1645.93
   242.3 1646.16   271.4 1646.47   290.7  1646.9   300.4 1647.23   348.9 1649.29
   358.6 1649.62
#Mann= 3 , 0 , 0
       0      .1       0    77.5    .045       0   106.6      .1       0
Bank Sta=77.5,106.6
XS Rating Curve= 0 ,0
Exp/Cntr=0.3,0.1

Type RM Length L Ch R = 1 ,8647.9  ,426.4,425.6,424.1
XS GIS Cut Line= 2
     1906821.753      299787.312     1906699.357      299490.437
#Sta/Elev= 23
       0 1668.66    19.5  1658.4    29.2 1653.19    38.9 1647.75    48.6 1641.64
    58.4  1634.9    68.1 1630.29    77.8 1629.74      88 1631.03    97.3 1632.12
     107 1632.72     146 1633.98   155.7 1634.21   165.4 1634.31   175.2  1634.2
   243.3 1632.76   262.7 1632.46   272.5 1632.53   282.2 1633.08   291.9 1635.14
   301.6  1638.7   311.4 1643.17   321.1 1648.24
#Mann= 3 , 0 , 0
       0      .1       0    68.1    .045       0      88      .1       0
#XS Ineff= 2 , 0
                          166.13         1634.55
Permanent Ineff=
       F       F
Bank Sta=68.1,88
XS Rating Curve= 0 ,0
Exp/Cntr=0.3,0.1

Type RM Length L Ch R = 1 ,8222.2  ,311.1,304.3,297.4
XS GIS Cut Line= 2
     1907204.565       299605.02     1907118.628      299422.729
#Sta/Elev= 24
       0 1646.38     9.6 1638.54    19.2 1628.73    28.8 1618.77    38.4 1611.56
      48  1607.8    57.6 1605.59    67.2 1604.09      76 1603.83    76.8 1603.81
    86.4 1605.44      91 1607.25      96 1609.22   105.6 1612.92   115.2 1616.01
   124.8 1618.33   134.4 1620.15     144 1621.85   153.6 1623.46   163.2 1623.68
   172.7 1621.84   182.3 1618.46   191.9 1615.63   201.5 1614.43
#Mann= 3 , 0 , 0
       0      .1       0    57.6    .045       0    86.4      .1       0
Bank Sta=57.6,86.4
XS Rating Curve= 0 ,0
Exp/Cntr=0.3,0.1

Type RM Length L Ch R = 1 ,7917.9  ,268.9,277.8,286.9
XS GIS Cut Line= 2
     1907467.586      299409.708     1907347.794      299279.499
#Sta/Elev= 22
       0 1635.83     9.8 1631.03    19.7 1626.36    29.5 1621.67    39.3 1617.02
    49.2 1612.28      59 1606.89    68.8  1601.4   74.93 1599.24    78.6 1597.99
    86.8 1597.94    88.5 1597.93    98.3 1599.69   101.8  1600.6   108.1 1602.23
     118  1604.1   127.8 1605.39   137.6 1606.08   147.4 1606.42   157.3 1606.65
   167.1 1606.88   176.9 1606.93
#Mann= 3 , 0 , 0
       0      .1       0   74.93    .045       0    98.3      .1       0
Bank Sta=74.93,98.3
XS Rating Curve= 0 ,0
Exp/Cntr=0.3,0.1

Type RM Length L Ch R = 1 ,7640.1  ,297.4,248.8,184
XS GIS Cut Line= 3
      1907657.69      299240.437     1907623.836      299196.166
     1907579.565       299073.77
#Sta/Elev= 23
       0 1622.73     9.3  1615.5    18.6 1608.87    27.9 1603.17    37.2 1599.21
    46.4 1596.66    55.7 1594.64      65 1592.52    74.3 1590.66      80 1589.92
    83.6 1589.46    92.9 1588.87      95 1589.02   102.2 1589.54   111.5 1592.61
   120.8 1594.75   130.1 1595.86   139.4 1596.66   148.7 1597.09     158 1597.18
   167.3  1597.3   176.6 1597.63   185.9 1598.13
#Mann= 3 , 0 , 0
       0      .1       0      80    .045       0   102.2      .1       0
Bank Sta=80,102.2
XS Rating Curve= 0 ,0
Exp/Cntr=0.3,0.1

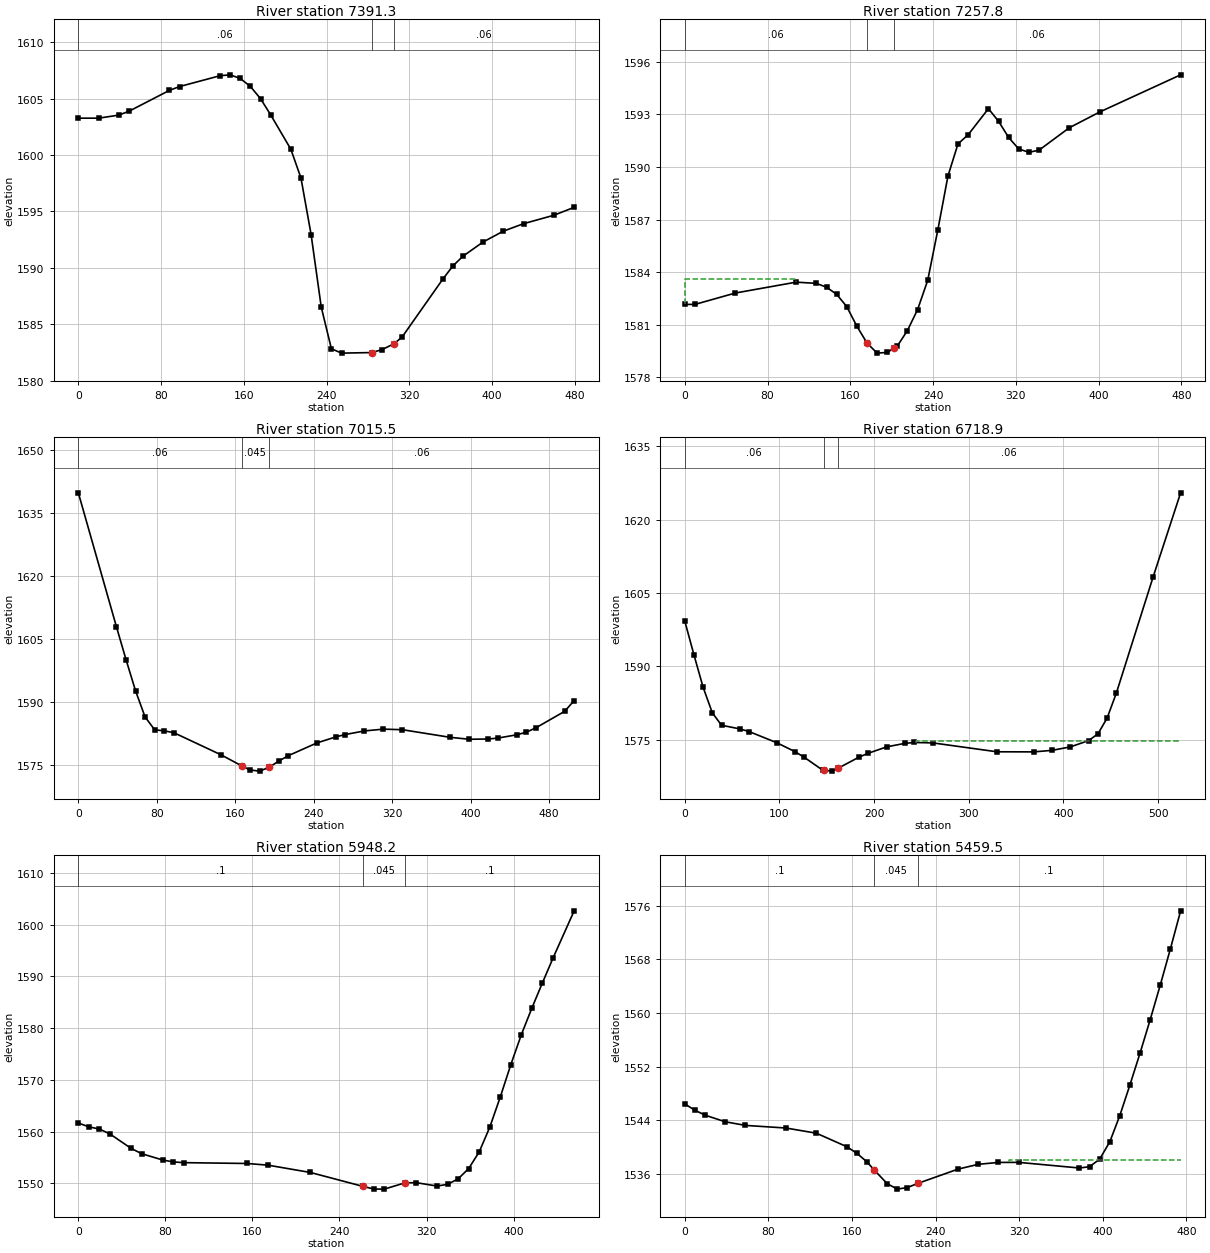
Type RM Length L Ch R = 1 ,7391.3  ,127.7,133.5,161.1
XS GIS Cut Line= 2
     1908147.273      299099.812     1907668.107      299086.791
#Sta/Elev= 30
       0 1603.27    19.6 1603.27    39.1 1603.54    48.9 1603.88      88 1605.73
    97.8 1606.07     137 1607.03   146.7 1607.11   156.5 1606.79   166.3 1606.08
   176.1    1605   185.9 1603.57   205.4 1600.52   215.2 1597.97     225 1592.96
   234.8 1586.54   244.6 1582.84   254.4 1582.45   283.7  1582.5   293.5 1582.76
   305.2 1583.28     313 1583.88   352.2 1588.99     362 1590.17   371.7 1591.03
   391.3  1592.3   410.9 1593.26   430.4 1593.92   459.8 1594.67   479.3 1595.37
#Mann= 3 , 0 , 0
       0     .06       0   283.7    .045       0   305.2     .06       0
Bank Sta=283.7,305.2
XS Rating Curve= 0 ,0
Exp/Cntr=0.3,0.1

Type RM Length L Ch R = 1 ,7257.8  ,199.9,242.2,278.8
XS GIS Cut Line= 2
     1908160.294      299032.104     1907681.128      299019.083
#Sta/Elev= 30
       0 1582.16     9.8 1582.16    48.9 1582.81   107.6 1583.43   127.2 1583.36
     137 1583.14   146.7 1582.74   156.5 1582.04   166.3 1580.92   176.1 1579.96
   185.9 1579.38   195.6 1579.42   201.9 1579.65   205.4 1579.78   215.2 1580.67
     225 1581.86   234.8 1583.53   244.6 1586.41   254.4 1589.49   264.1 1591.32
   273.9 1591.84   293.5 1593.33   303.3 1592.61     313 1591.69   322.8 1591.03
   332.6 1590.84   342.4 1590.96   371.7 1592.24   401.1 1593.14   479.3 1595.26
#Mann= 3 , 0 , 0
       0     .06       0   176.1    .045       0   201.9     .06       0
#XS Ineff= 2 , 0
          107.04 1583.59
Permanent Ineff=
       F       F
Bank Sta=176.1,201.9
XS Rating Curve= 0 ,0
Exp/Cntr=0.3,0.1

Type RM Length L Ch R = 1 ,7015.5  ,296.9,296.6,296.3
XS GIS Cut Line= 2
     1908259.253      299125.854     1908076.961      298654.499
#Sta/Elev= 30
       0 1639.82    38.9 1607.91    48.6 1600.15    58.3 1592.74      68 1586.52
    77.8 1583.45    87.5  1583.2    97.2 1582.78   145.8 1577.46   166.6 1574.86
   174.9  1573.9   184.7 1573.62   194.4 1574.52   204.1 1575.98   213.8 1577.27
     243 1580.31   262.4 1581.76   272.1 1582.33   291.6 1583.18     311 1583.61
   330.4 1583.47     379 1581.66   398.5  1581.2   417.9 1581.26   427.6 1581.48
   447.1 1582.27   456.8 1582.89   466.5 1583.94   495.7 1587.84   505.4  1590.4
#Mann= 3 , 0 , 0
       0     .06       0   166.6    .045       0   194.4     .06       0
Bank Sta=166.6,194.4
XS Rating Curve= 0 ,0
Exp/Cntr=0.3,0.1

Type RM Length L Ch R = 1 ,6718.9  ,769.4,770.7,771.9
XS GIS Cut Line= 2
     1908514.461      298969.604     1908308.732      298487.833
#Sta/Elev= 30
       0 1599.25     9.7 1592.34    19.4 1585.71    29.1 1580.52    38.8 1577.99
    58.2 1577.24    67.9  1576.7      97 1574.44   116.4  1572.6   126.1 1571.46
   145.5 1568.84   146.7 1568.81   155.2 1568.62   161.7 1569.18   184.3  1571.5
     194 1572.28   213.4 1573.58   232.8  1574.3   242.5 1574.47   261.9 1574.39
   329.8 1572.57   368.6 1572.55     388 1572.86   407.4 1573.57   426.8 1574.86
   436.6 1576.25   446.2 1579.44     456 1584.57   494.8 1608.25   523.9 1625.45
#Mann= 3 , 0 , 0
       0     .06       0   146.7    .045       0   161.7     .06       0
#XS Ineff= 2 , 0
                          244.23         1574.77
Permanent Ineff=
       F       F
Bank Sta=146.7,161.7
XS Rating Curve= 0 ,0
Exp/Cntr=0.3,0.1

Type RM Length L Ch R = 1 ,5948.2  ,476.8,488.7,500.5
XS GIS Cut Line= 2
     1909136.857      298628.458     1908978.003      298201.374
#Sta/Elev= 30
       0 1561.67     9.7 1560.92    19.4  1560.5    29.1 1559.54    48.5 1556.76
    58.2 1555.73    77.6 1554.51    87.3 1554.14      97    1554   155.1 1553.84
   174.5 1553.51   213.3  1552.1   261.8  1549.4   271.5  1548.9   281.2 1548.88
   299.8 1550.07   310.2 1550.14   329.6 1549.48   339.3  1549.8     349 1550.86
   358.7 1552.84   368.4 1556.07   378.1 1560.83   387.8  1566.7   397.5 1572.96
   407.2 1578.78   416.9 1583.92   426.6 1588.81   436.3 1593.58   455.7  1602.7
#Mann= 3 , 0 , 0
       0      .1       0   261.8    .045       0   299.8      .1       0
Bank Sta=261.8,299.8
XS Rating Curve= 0 ,0
Exp/Cntr=0.3,0.1

Type RM Length L Ch R = 1 ,5459.5  ,722.8,715.8,708.9
XS GIS Cut Line= 2
      1909476.83      298504.743     1909558.732      298037.312
#Sta/Elev= 30
       0 1546.44     9.7  1545.5    19.4 1544.77    38.7 1543.78    58.1 1543.24
    96.8 1542.85   125.9 1542.08     155 1540.07   164.6  1539.1   174.3 1537.81
   181.3  1536.6   193.7 1534.56   203.4 1533.74   213.1 1533.98   222.8 1534.58
   261.5 1536.72   280.9 1537.44   300.2 1537.72   319.6 1537.73   377.7 1536.89
   387.4 1537.08   397.1 1538.21   406.8 1540.79   416.4 1544.71   426.1 1549.29
   435.8 1554.04   445.5 1559.02   455.2 1564.21   464.9 1569.61   474.6 1575.23
#Mann= 3 , 0 , 0
       0      .1       0   181.3    .045       0   222.8      .1       0
#XS Ineff= 2 , 0
                          310.56         1538.14
Permanent Ineff=
       F       F
Bank Sta=181.3,222.8
XS Rating Curve= 0 ,0
Exp/Cntr=0.3,0.1