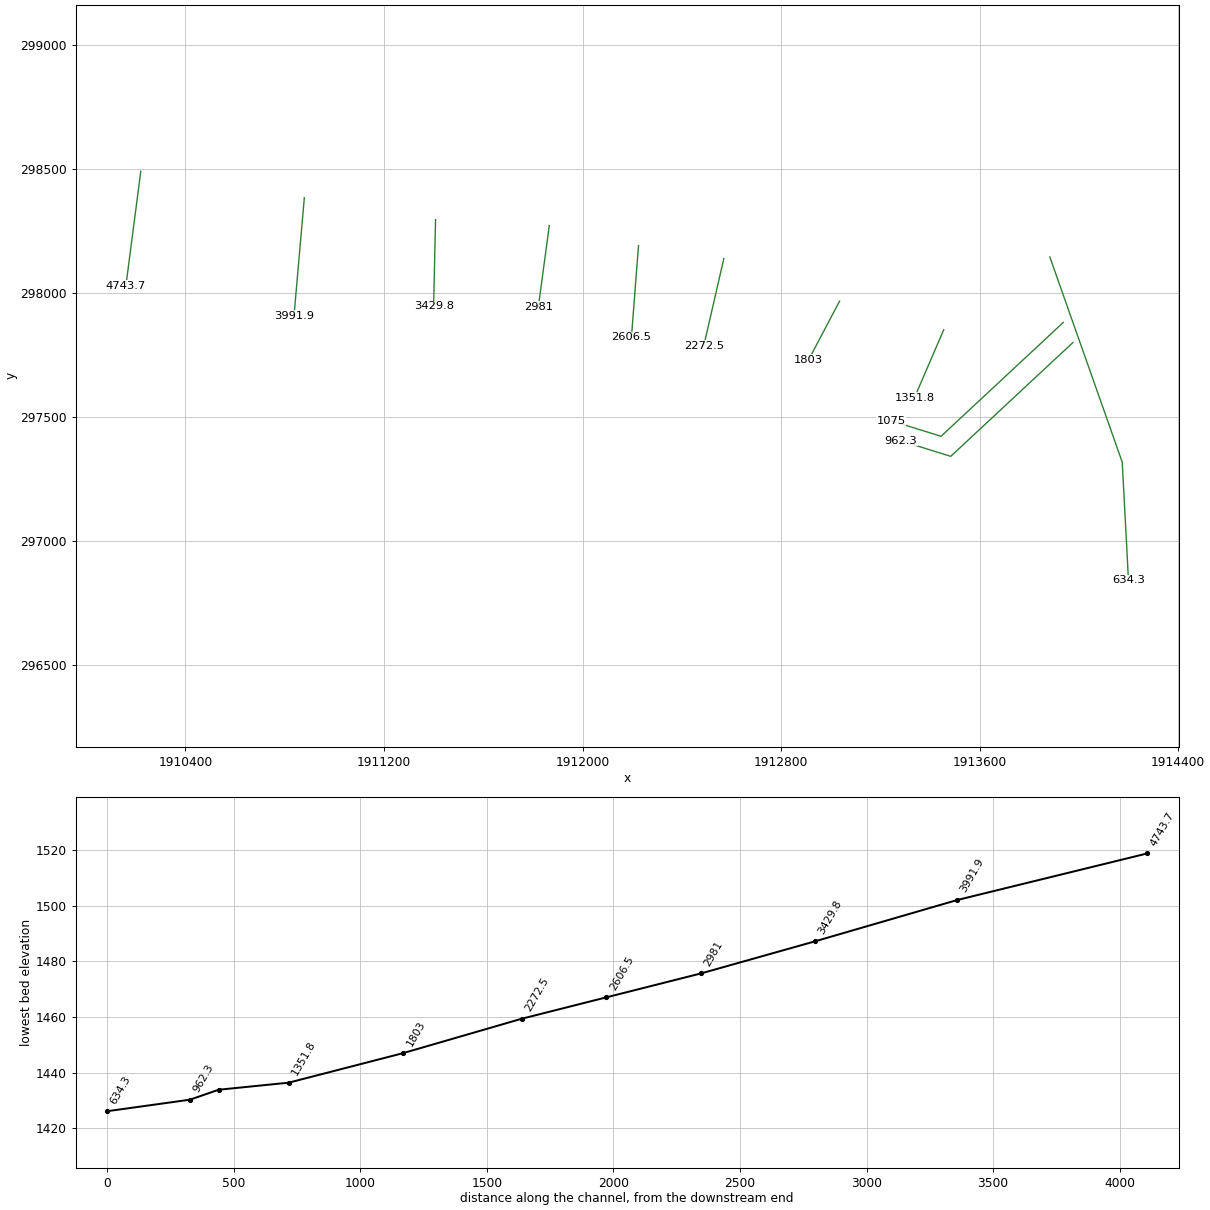
HEC-RAS study FLAGRN.prj: FLAGRN

--- FLAGRN.g01 (geometry) --- (continued)

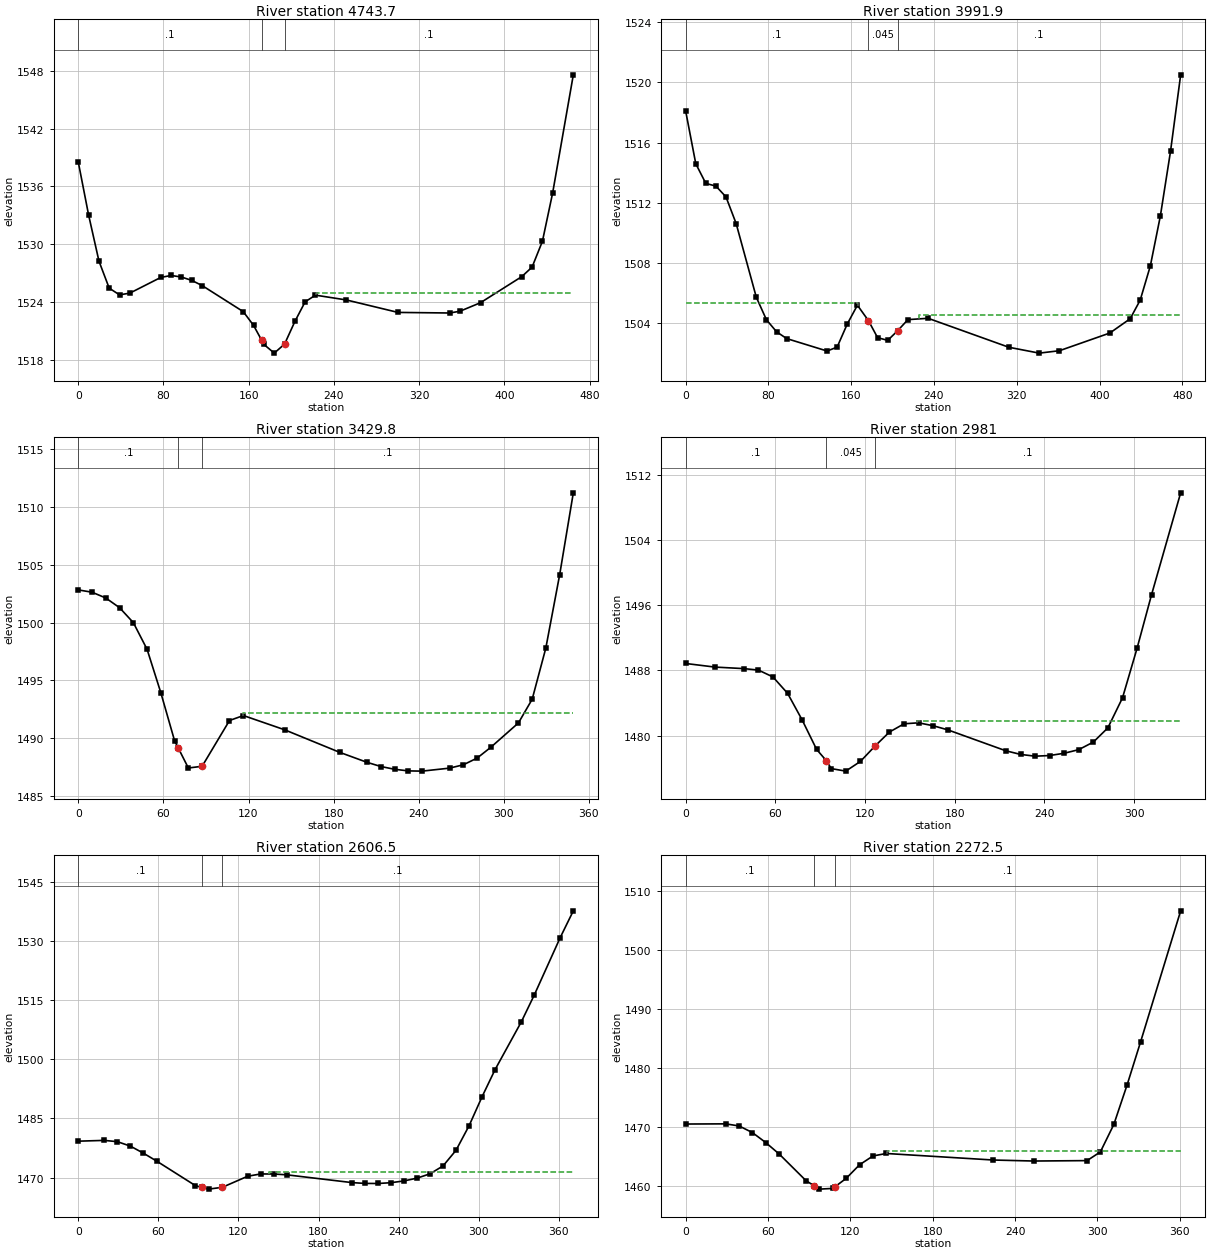
Type RM Length L Ch R = 1 ,4743.7  ,751.4,751.8,752
XS GIS Cut Line= 2
      1910220.19      298490.437     1910160.294      298029.499
#Sta/Elev= 30
       0 1538.52     9.7 1533.03    19.4 1528.26      29 1525.46    38.7 1524.76
    48.4 1524.94    77.5 1526.57    87.2 1526.77    96.8 1526.61   106.5 1526.26
   116.2 1525.73   154.9 1523.02   164.6 1521.59   172.3 1520.03   174.3 1519.62
     184 1518.72   193.7 1519.66   203.4 1522.01     213 1524.04   222.7 1524.73
   251.8 1524.23   300.2 1522.94   348.6 1522.88   358.3 1523.06   377.7 1523.95
   416.4 1526.65   426.1 1527.64   435.8 1530.32   445.4 1535.33   464.8 1547.57
#Mann= 3 , 0 , 0
       0      .1       0   172.3    .045       0   193.7      .1       0
#XS Ineff= 2 , 0
                          223.24         1524.94
Permanent Ineff=
       F       F
Bank Sta=172.3,193.7
XS Rating Curve= 0 ,0
Exp/Cntr=0.3,0.1

Type RM Length L Ch R = 1 ,3991.9  ,560.4,562.1,563.7
XS GIS Cut Line= 2
     1910879.044      298383.666     1910837.378      297907.104
#Sta/Elev= 30
       0 1518.11     9.8 1514.59    19.5 1513.28    29.3  1513.1      39 1512.38
    48.8 1510.61    68.3  1505.7    78.1  1504.2    87.9  1503.4    97.6 1502.95
   136.7 1502.12   146.4 1502.38   156.2 1503.92     166 1505.17   176.7 1504.14
   185.5 1503.01   195.3 1502.83     205 1503.48   214.8 1504.21   234.3  1504.3
   312.4 1502.37   341.7 1501.98   361.2 1502.14     410 1503.32   429.6 1504.27
   439.3 1505.51   449.1 1507.79   458.8 1511.12   468.6 1515.42   478.4 1520.51
#Mann= 3 , 0 , 0
       0      .1       0   176.7    .045       0     205      .1       0
#XS Ineff= 2 , 0
           166.2 1505.31  225.35         1504.55
Permanent Ineff=
       F       F
Bank Sta=176.7,205
XS Rating Curve= 0 ,0
Exp/Cntr=0.3,0.1

Type RM Length L Ch R = 1 ,3429.8  ,451.3,448.8,446.3
XS GIS Cut Line= 2
      1911407.69      298295.124     1911399.878      297946.166
#Sta/Elev= 29
       0 1502.82     9.7 1502.62    19.4 1502.12    29.1 1501.28    38.8 1499.99
    48.5 1497.68    58.2 1493.92    67.9 1489.76    70.6 1489.11    77.6 1487.41
    87.3 1487.56   106.6 1491.52   116.4 1491.95   145.4 1490.72   184.2 1488.77
   203.6  1487.9   213.3 1487.54     223  1487.3   232.7 1487.16   242.4 1487.14
   261.8  1487.4   271.5 1487.69   281.2 1488.27   290.9 1489.21   310.3 1491.31
     320 1493.36   329.6 1497.78   339.4 1504.15     349 1511.22
#Mann= 3 , 0 , 0
       0      .1       0    70.6    .045       0    87.3      .1       0
#XS Ineff= 2 , 0
                          116.34         1492.16
Permanent Ineff=
       F       F
Bank Sta=70.6,87.3
XS Rating Curve= 0 ,0
Exp/Cntr=0.3,0.1

Type RM Length L Ch R = 1 ,2981    ,373.2,374.5,375.7
XS GIS Cut Line= 2
     1911866.023      298271.687     1911821.753      297943.562
#Sta/Elev= 30
       0 1488.85    19.5 1488.41      39 1488.22    48.7 1488.04    58.4  1487.2
    68.2 1485.19    77.9 1481.94    87.6 1478.32   94.15 1476.93    97.4 1475.97
   107.1 1475.66   116.9 1476.85   126.6 1478.72   136.3 1480.45   146.1 1481.46
   155.8 1481.58   165.6 1481.22   175.3 1480.72   214.2 1478.15     224 1477.71
   233.7 1477.49   243.4 1477.57   253.2 1477.85   262.9 1478.29   272.7 1479.22
   282.4 1480.96   292.2 1484.64   301.9 1490.69   311.6 1497.26   331.1 1509.76
#Mann= 3 , 0 , 0
       0      .1       0   94.15    .045       0   126.6      .1       0
#XS Ineff= 2 , 0
                          154.79         1481.81
Permanent Ineff=
       F       F
Bank Sta=94.15,126.6
XS Rating Curve= 0 ,0
Exp/Cntr=0.3,0.1

Type RM Length L Ch R = 1 ,2606.5  ,337.3,334,330.7
XS GIS Cut Line= 2
     1912225.398      298190.958     1912196.753      297821.166
#Sta/Elev= 30
       0 1479.23    19.5 1479.43    29.3  1479.1      39 1477.98    48.8 1476.18
    58.6  1474.2    87.8 1467.94    92.9 1467.48    97.6 1467.06   107.9 1467.52
   126.9 1470.33   136.6 1470.91   146.4  1470.9   156.2 1470.69     205 1468.72
   214.7 1468.51   224.5 1468.49   234.2 1468.69     244 1469.14   253.8 1469.85
   263.5 1470.94   273.3 1472.95     283 1476.91   292.8 1483.15   302.6 1490.56
   312.3 1497.41   331.9 1509.49   341.6 1516.29   361.1 1530.91   370.9 1537.69
#Mann= 3 , 0 , 0
       0      .1       0    92.9    .045       0   107.9      .1       0
#XS Ineff= 2 , 0
                           143.1         1471.37
Permanent Ineff=
       F       F
Bank Sta=92.9,107.9
XS Rating Curve= 0 ,0
Exp/Cntr=0.3,0.1

Type RM Length L Ch R = 1 ,2272.5  ,475.4,469.6,463.7
XS GIS Cut Line= 2
     1912569.148      298138.874     1912488.419      297787.312
#Sta/Elev= 23
       0 1470.44    29.2 1470.47      39 1470.11    48.7 1468.98    58.5 1467.27
    68.2 1465.34    87.7 1460.83    93.7 1459.95    97.5 1459.39   107.2 1459.51
   108.7 1459.77     117 1461.22   126.7 1463.52   136.5 1465.02   146.2 1465.44
   224.2 1464.33   253.5 1464.16   292.5 1464.23   302.2 1465.71     312 1470.37
   321.7  1477.1   331.5 1484.39   360.7 1506.63
#Mann= 3 , 0 , 0
       0      .1       0    93.7    .045       0   108.7      .1       0
#XS Ineff= 2 , 0
                          146.48         1465.81
Permanent Ineff=
       F       F
Bank Sta=93.7,108.7
XS Rating Curve= 0 ,0
Exp/Cntr=0.3,0.1

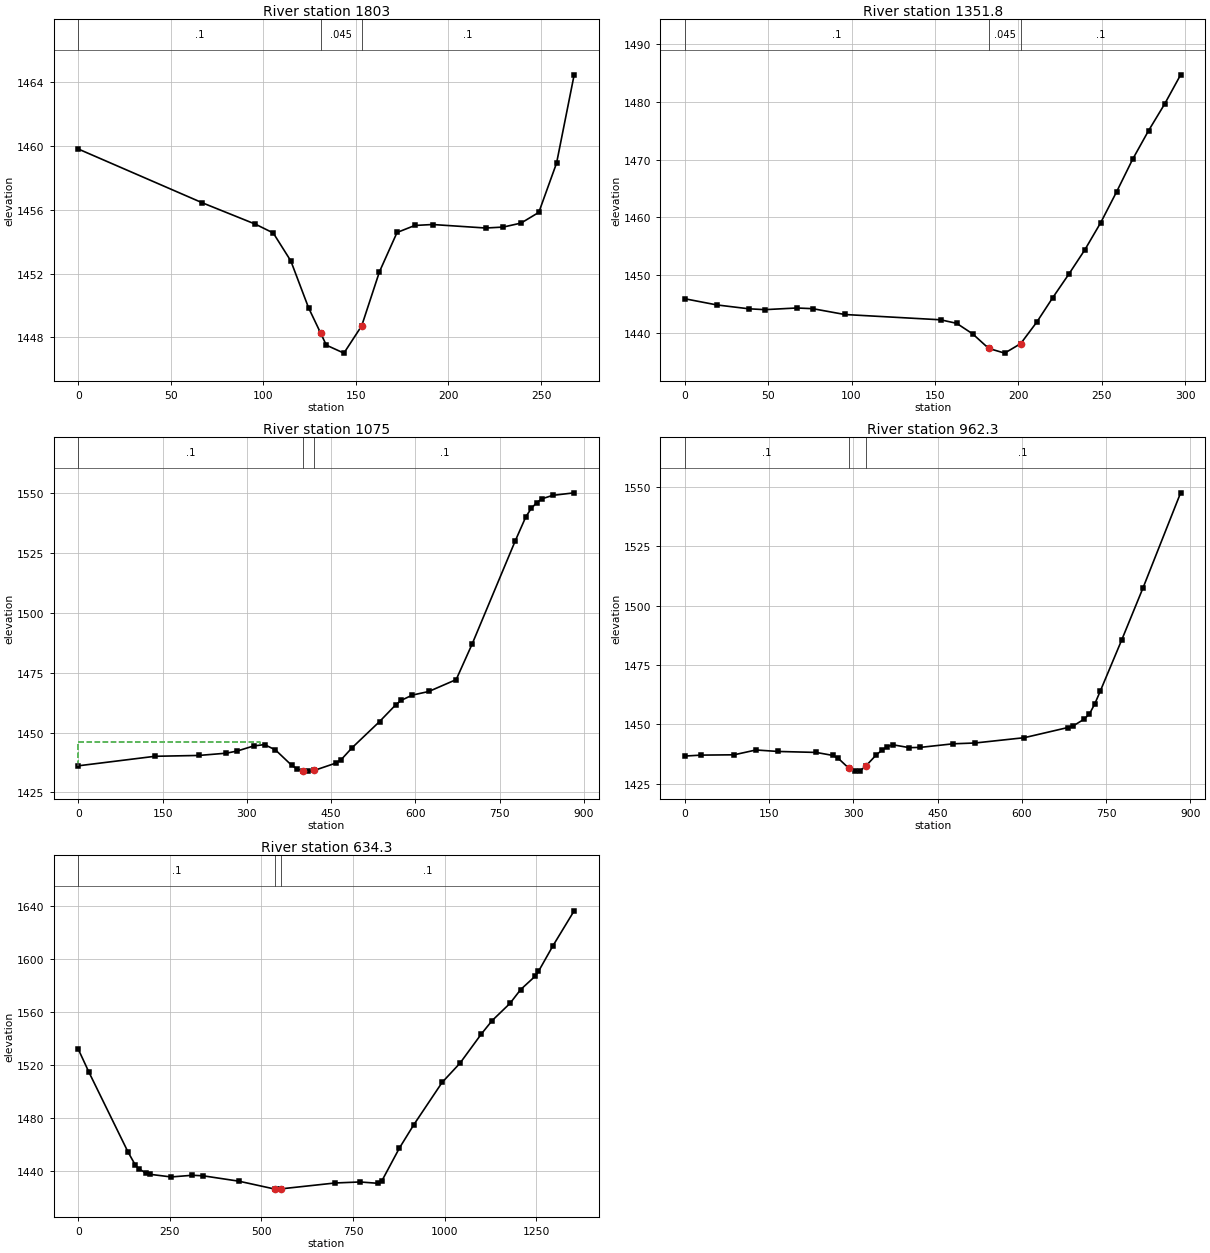
Type RM Length L Ch R = 1 ,1803    ,449.2,451.1,453.1
XS GIS Cut Line= 2
     1913035.294      297966.999     1912910.294       297730.02
#Sta/Elev= 20
       0 1459.81      67 1456.44    95.7  1455.1   105.3 1454.55   114.8  1452.8
   124.4 1449.86   130.9 1448.28     134 1447.52   143.5 1447.02   153.1 1448.73
   162.7 1452.12   172.2 1454.58   181.8 1455.02   191.4 1455.08   220.1 1454.86
   229.6 1454.92   239.2 1455.17   248.8 1455.84   258.4 1458.93   267.9 1464.46
#Mann= 3 , 0 , 0
       0      .1       0   130.9    .045       0   153.1      .1       0
Bank Sta=130.9,153.1
XS Rating Curve= 0 ,0
Exp/Cntr=0.3,0.1

Type RM Length L Ch R = 1 ,1351.8  ,293.2,276.9,256.5
XS GIS Cut Line= 2
     1913455.115       297851.98     1913337.378      297578.979
#Sta/Elev= 23
       0 1445.87    19.2  1444.8    38.4 1444.13      48 1443.98    67.1 1444.27
    76.7 1444.15    95.9 1443.14   153.4 1442.22     163 1441.61   172.6 1439.78
   182.2 1437.26   191.8 1436.44   201.4 1438.09     211  1441.8   220.6 1446.05
   230.2 1450.11   239.8 1454.33   249.4 1459.08     259 1464.47   268.5 1470.05
   278.1 1475.04   287.7 1479.64   297.3 1484.71
#Mann= 3 , 0 , 0
       0      .1       0   182.2    .045       0   201.4      .1       0
Bank Sta=182.2,201.4
XS Rating Curve= 0 ,0
Exp/Cntr=0.3,0.1

Type RM Length L Ch R = 1 ,1075    ,106.9,112.7,122.2
XS GIS Cut Line= 3
     1913936.336      297881.062     1913444.148      297422.729
     1913243.628      297485.229
#Sta/Elev= 30
       0 1436.12   136.5 1440.09   214.4 1440.44   263.2 1441.38   282.7 1442.28
   311.9 1444.39   331.4 1444.97   350.9 1442.74   380.1 1436.25   389.9 1434.76
   399.6 1433.99   409.4  1433.9   420.3 1434.22   458.1 1437.23   467.9  1438.7
   487.4 1443.68   536.1 1454.55   565.3 1461.63   575.1 1463.47   594.6 1465.62
   623.8 1467.12   672.6 1472.08   701.2 1487.03   777.6 1529.87   796.7 1540.04
   806.2 1543.46   815.8 1545.87   825.3  1547.5   844.4 1548.93   882.6 1549.99
#Mann= 3 , 0 , 0
       0      .1       0   399.6    .045       0   420.3      .1       0
#XS Ineff= 2 , 0
          322.54 1445.88
Permanent Ineff=
       F       F
Bank Sta=399.6,420.3
XS Rating Curve= 0 ,0
Exp/Cntr=0.3,0.1

Type RM Length L Ch R = 1 ,962.3   ,300.4,328,355.8
XS GIS Cut Line= 3
     1913975.398      297800.333     1913483.211      297341.999
      1913282.69      297404.499
#Sta/Elev= 30
       0 1436.68    29.2 1437.08    87.7 1437.21   126.7 1439.24   165.7 1438.62
   233.9 1438.21   263.2 1436.96   272.9 1435.78   292.4 1431.46   302.2 1430.34
   311.9 1430.46   321.9  1432.4   341.2 1437.27   350.9 1439.12   360.6 1440.69
   370.4 1441.43   399.6 1440.22   419.1 1440.33   477.6 1441.84   516.6 1442.18
   604.3 1444.41   682.1  1448.7   691.6  1449.4   710.7 1452.19   720.3  1454.4
   729.8 1458.64   739.4 1463.92   777.6 1485.47   815.8 1507.54   882.6 1547.46
#Mann= 3 , 0 , 0
       0      .1       0   292.4    .045       0   321.9      .1       0
Bank Sta=292.4,321.9
XS Rating Curve= 0 ,0
Exp/Cntr=0.3,0.1

Type RM Length L Ch R = 1 ,634.3   ,635.6,634.3,632.9
XS GIS Cut Line= 3
     1913882.516      298144.951     1914174.183      297318.562
     1914199.357      296841.999
#Sta/Elev= 30
       0 1531.94    29.2 1514.48   136.3 1453.91   155.8 1444.33   165.5 1441.61
     185 1438.14   194.7 1437.43   253.2 1435.41   311.6 1436.67   340.8 1436.26
   438.2  1432.2   535.6 1426.29   545.3 1426.19   554.5 1426.43   701.1 1430.84
   769.2 1431.61   817.9 1430.59   827.7 1431.96   876.4 1457.19   915.3 1474.68
   993.2 1506.93  1041.9 1521.44  1100.4  1543.6  1129.6 1553.65  1178.3 1566.65
  1207.5 1577.13  1246.4 1587.04  1256.2 1590.88  1295.1 1609.98  1353.6 1636.69
#Mann= 3 , 0 , 0
       0      .1       0   535.6    .045       0   554.5      .1       0
Bank Sta=535.6,554.5
XS Rating Curve= 0 ,0
Exp/Cntr=0.3,0.1

Chan Stop Cuts=-1
Use User Specified Reach Order=0
Composite Channel Slope=5